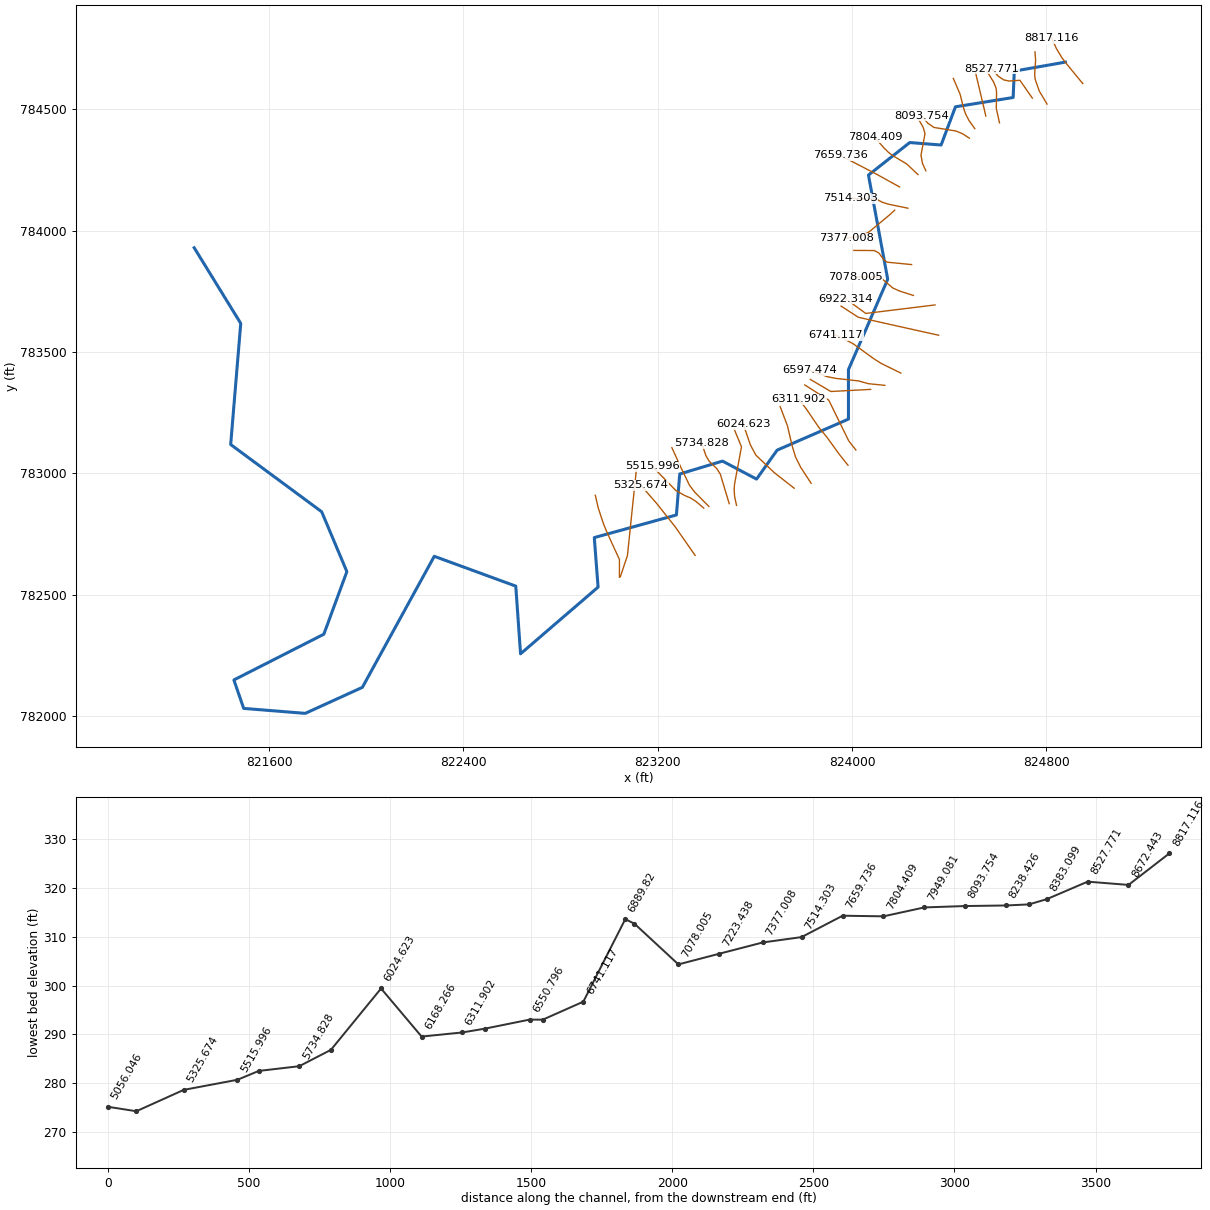
--- 17386_ras.prj (project) ---

Proj Title=17386
Current Plan=p01
Default Exp/Contr=0.3,0.1
English Units
Geom File=g01
Flow File=f01
Plan File=p01
Y Axis Title=Elevation
X Axis Title(PF)=Main Channel Distance
X Axis Title(XS)=Station
BEGIN DESCRIPTION:
RFD model 17386 exported to HEC-RAS
END DESCRIPTION:

--- 17386_ras.p01 (plan) ---

Plan Title=Plan 01
Program Version=4.10
Short Identifier=Plan 01
Geom File=g01
Flow File=f01
Subcritical Flow
Calc Critical at every XS
Secant Critical Depth

--- 17386_ras.f01 (steady flow) ---

Flow Title=Flow 01
Program Version=5.01
Number of Profiles= 6
Profile Names=10yr,25yr,50yr,100yr,100plus,500yr
River Rch & RM=17386,35,8817.116
  144.78  232.42  314.39  389.67  568.92 1014.79
River Rch & RM=17386,35,7804.409
  151.98   244.1  330.32  409.52   597.9 1059.62
River Rch & RM=17386,35,7659.736
  153.98  247.34  334.73  415.02  605.93 1071.95
River Rch & RM=17386,35,7514.303
  156.37  251.22  340.02   421.6  615.53 1086.66
River Rch & RM=17386,35,7223.438
  169.07  271.77  367.99   456.4  666.35 1163.87
River Rch & RM=17386,35,7078.005
  170.63  274.31  371.44  460.71  672.63 1173.37
River Rch & RM=17386,35,6922.314
  204.07  328.31  444.88  551.98  805.88 1371.13
River Rch & RM=17386,35,6741.117
  210.81  339.26   459.8  570.57  833.03 1411.09
River Rch & RM=17386,35,6597.474
  212.68  342.28  463.93  575.71  840.54 1422.11
River Rch & RM=17386,35,6391.737
  232.49  374.34  507.56  629.97  919.76 1536.95
River Rch & RM=17386,35,6168.266
  236.51  380.85  516.45  641.05  935.94 1560.36
River Rch & RM=17386,35,6024.623
  239.05  384.99  522.09  648.08   946.2 1575.18
River Rch & RM=17386,35,5847.086
  245.32  395.12  535.87  665.22  971.22 1610.96
River Rch & RM=17386,35,5591.219
   246.8  397.51  539.12  669.25   977.1 1619.33
River Rch & RM=17386,35,5515.996
  251.46  405.09  549.47  682.16  995.96 1646.43
Boundary for River Rch & Prof#=17386,35,1
Up Type= 0
Dn Type= 2
Boundary for River Rch & Prof#=17386,35,2
Up Type= 0
Dn Type= 2
Boundary for River Rch & Prof#=17386,35,2
Up Type= 0
Dn Type= 2
Boundary for River Rch & Prof#=17386,35,2
Up Type= 0
Dn Type= 2
Boundary for River Rch & Prof#=17386,35,2
Up Type= 0
Dn Type= 2
Boundary for River Rch & Prof#=17386,35,2
Up Type= 0
Dn Type= 2

--- 17386_ras.g01 (geometry) ---

Geom Title=17386
Program Version=4.10

River Reach=17386,35
Reach XY= 30
824878.242459208784693.241026893824667.574836463784656.155158713
824662.867726028784547.534578994 824425.37917617784509.259794712
824366.274758726784351.964178458824237.162601054784362.118961275
824067.216720432784228.186588854824146.508009315783799.272191942
823984.834682137783427.194215536823984.849506229783223.633722037
823691.228466988783095.821225747  823606.6302917 782976.76757592
823466.455244154783050.744752884 823290.41334331782997.749440208
823276.681574762782829.078589946822938.720368981782735.899957404
822954.227544963782531.995640233822635.098605335782257.528146327
 822615.43669048782536.175297335822279.898341835782658.877319455
821983.937787354782119.456976831821748.914199501782012.307576925
821495.420408756782032.797837183821455.025324315 782149.88503845
821825.361657292782338.166473731821920.100025773782595.768046394
821816.404947817782842.308010578821441.849458545 783119.00547497
821483.267971843783617.610614777 821291.70582661 783928.93610388

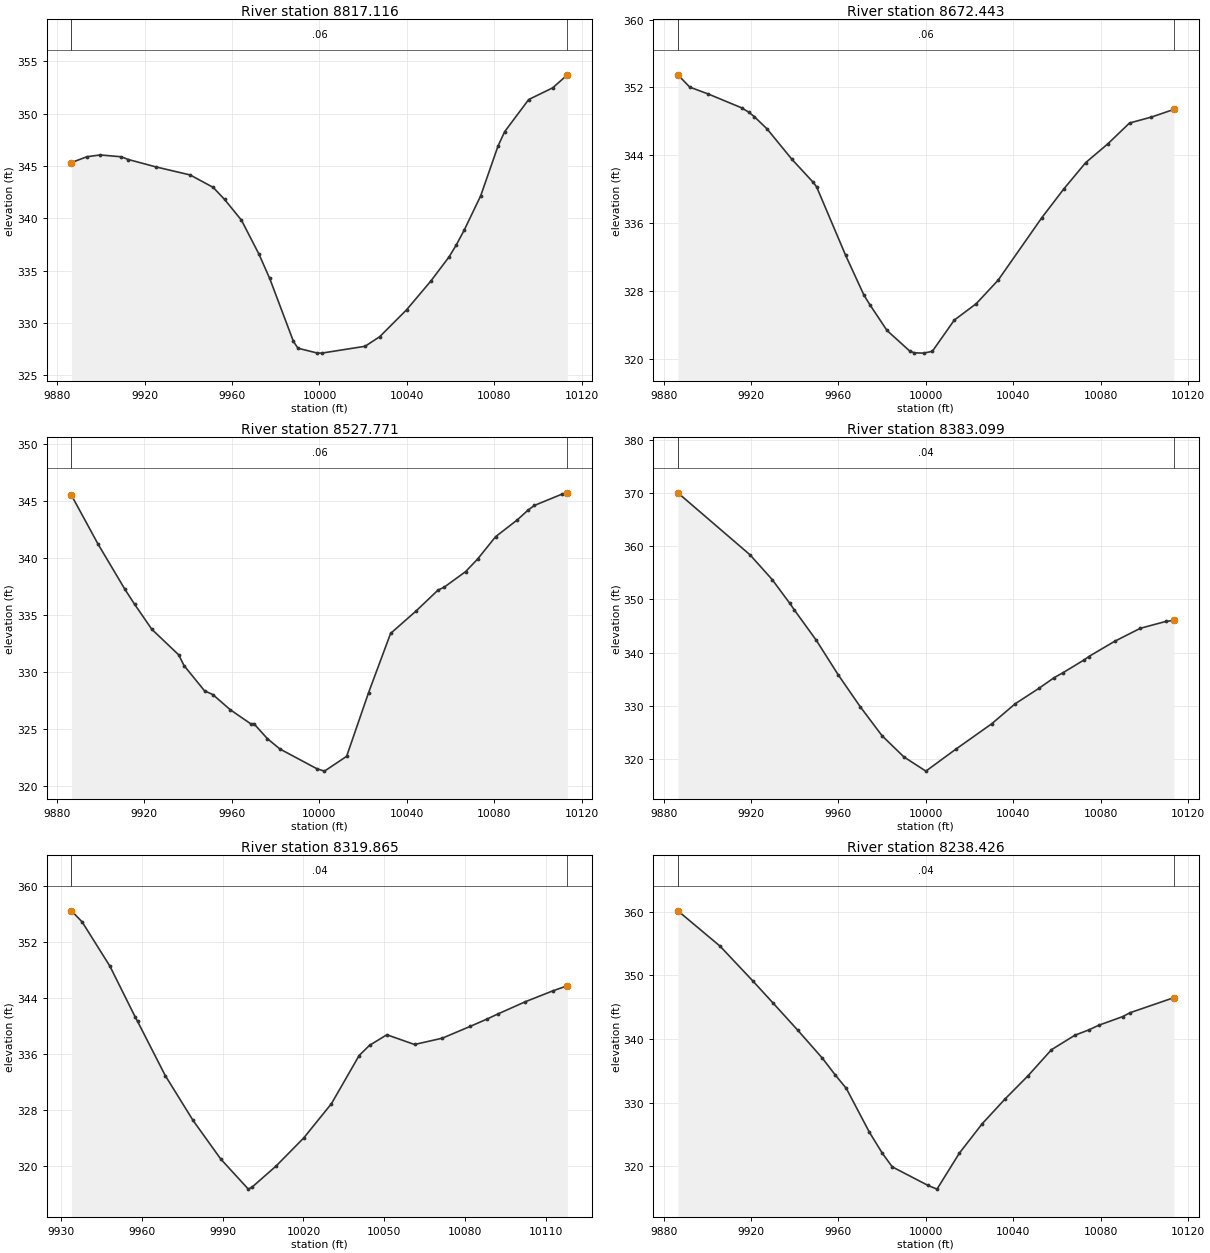
Type RM Length L Ch R = 1 ,8817.116,144.672500,144.672500,144.672500
XS GIS Cut Line= 6
824949.451107965784604.842422196824878.082250075784691.835917277
824876.837349592784693.401236026824863.232140607784711.786757271
824841.460333691784748.128535411824821.827402013784791.096107183
#Sta/Elev= 29
9886.477345.31729893.495345.87359899.616346.04759909.261345.8708 9912.55 345.609
9925.028344.90949940.794344.13649951.354342.9469 9956.56341.79619964.289339.8142
9972.327336.55789977.223334.24139988.093328.22369990.158327.5783    9999327.1178
   10001327.1086 10020.9327.763510027.62328.687410039.89331.253310050.93333.9841
10059.35336.312910062.59337.431110066.24 338.85810073.79342.137410081.78346.9216
10084.79348.275710095.78351.341910106.77352.460310113.48353.7028
#Mann= 3 , 0 , 0
9886.477    0.06       09886.477    0.06       010113.48    0.06       0
#XS Ineff= 2 , 0
       0                               0
Bank Sta=9886.477,10113.48
Exp/Cntr=0.3,0.1

Type RM Length L Ch R = 1 ,8672.443,144.672400,144.672400,144.672400
XS GIS Cut Line= 6
 824802.40664015784520.412305815824770.658811037784573.613733536
824753.329690935784623.083919008 824751.46778142784641.844357761
824755.326129218784700.616195853824752.805888625784735.188989045
#Sta/Elev= 28
9886.511353.48599891.953352.03499900.285351.23579915.674349.59149918.881349.0889
9921.406348.56659927.294347.11189938.687343.51739948.501340.77929950.001340.2537
9963.291  332.179971.648327.48589974.307326.37589982.173323.32279992.601320.8875
9994.707320.6786    9999320.642410002.93 320.85510012.97 324.53910023.02326.4792
10033.04329.250410053.08336.6438 10063.1340.022810073.12343.128310083.15 345.321
10093.17347.8004 10103.2348.502110113.42349.4024
#Mann= 3 , 0 , 0
9886.511    0.06       09886.511    0.06       010113.42    0.06       0
#XS Ineff= 2 , 0
       0                               0
Bank Sta=9886.511,10113.42
Exp/Cntr=0.3,0.1

Type RM Length L Ch R = 1 ,8527.771,144.672500,144.672500,144.672500
XS GIS Cut Line= 6
 824741.77162413784545.104353128824690.663206601784618.477008214
824645.865145028784615.263537055824623.995046161784620.097707944
824600.659166939784635.940561099824573.824315984784666.830283771
#Sta/Elev= 30
9886.704345.48849898.868341.2056 9911.16337.24089915.543335.94489923.453333.7416
9935.745331.50019938.168330.56449947.572328.34599951.309328.02769959.285326.6984
 9968.77 325.4479970.072 325.4789976.284324.15779982.038323.2512    9999321.5152
10002.39321.314110012.51322.612610022.53328.186710032.61333.381110044.16335.3298
10054.28337.175510057.07337.427610066.91338.798210072.46339.914310080.58341.8521
10090.49343.324410095.46344.186110098.32344.593410111.09345.597610113.43345.7016
#Mann= 3 , 0 , 0
9886.704    0.06       09886.704    0.06       010113.43    0.06       0
#XS Ineff= 2 , 0
       0                               0
Bank Sta=9886.704,10113.43
Exp/Cntr=0.3,0.1

Type RM Length L Ch R = 1 ,8383.099,63.233800,63.233800,63.233800
XS GIS Cut Line= 6
824606.649563787784443.184866581824593.492295114784502.591951278
824594.640454106784568.595582172824592.796332467784585.557094012
824582.274553032 784611.57118858824553.390304104784657.995558875
#Sta/Elev= 23
9886.534  370.029919.518358.37729929.665353.72659937.767349.23419939.788348.0255
9949.884342.29279959.895335.81159969.906329.85829979.927324.37939989.956320.3891
9999.981317.727810013.59321.824810030.09326.624110040.84330.383810051.62333.2686
10058.71335.306310062.75336.230210072.48338.654510074.53339.2627 10086.3342.1152
10098.08344.566410109.86345.866710113.39346.0363
#Mann= 3 , 0 , 0
9886.534    0.04       09886.534    0.04       010113.39    0.04       0
#XS Ineff= 2 , 0
       0                               0
Bank Sta=9886.534,10113.39
Exp/Cntr=0.3,0.1

Type RM Length L Ch R = 1 ,8319.865,81.438700,81.438700,81.438700
XS GIS Cut Line= 2
824550.433920681784471.140000045824508.116212338784650.176458359
#Sta/Elev= 24
9933.929356.40949937.896  354.829948.171348.51649957.552341.26019958.447340.6185
9968.722332.87469978.998326.48799989.273320.96349999.549316.646510001.03 316.966
10009.82319.9402 10020.1 323.96110030.38 328.85910040.65335.7382 10044.5337.1898
10050.93338.7032 10061.2337.312510071.48 338.21210081.75339.883710087.97340.9235
10092.03341.6582 10102.3343.421710112.58344.9853 10117.9345.7067
#Mann= 3 , 0 , 0
9933.929    0.04       09933.929    0.04       0 10117.9    0.04       0
#XS Ineff= 2 , 0
       0                               0
Bank Sta=9933.929,10117.9
Exp/Cntr=0.3,0.1

Type RM Length L Ch R = 1 ,8238.426,144.672400,144.672400,144.672400
XS GIS Cut Line= 6
824504.945677973784419.270770039824481.373184316784452.466441246
824466.869766831784480.129170227824459.866127444784500.568341468
824444.001593006784562.485241757824416.611669278784626.260008698
#Sta/Elev= 24
9886.545360.15049905.836354.60279920.994 349.0799930.119345.6587 9941.41341.3929
9952.701336.98899958.493334.39519963.642332.24019974.212325.35569980.098322.0718
9984.645319.9262   10001317.010110005.13316.426110015.38322.088910025.78326.6841
10036.24330.577310046.77334.2268 10057.5338.328510068.24340.607410074.66341.4493
10079.09342.1658 10090.1343.529510093.45344.1386 10113.5346.5045
#Mann= 3 , 0 , 0
9886.545    0.04       09886.545    0.04       0 10113.5    0.04       0
#XS Ineff= 2 , 0
       0                               0
Bank Sta=9886.545,10113.5
Exp/Cntr=0.3,0.1

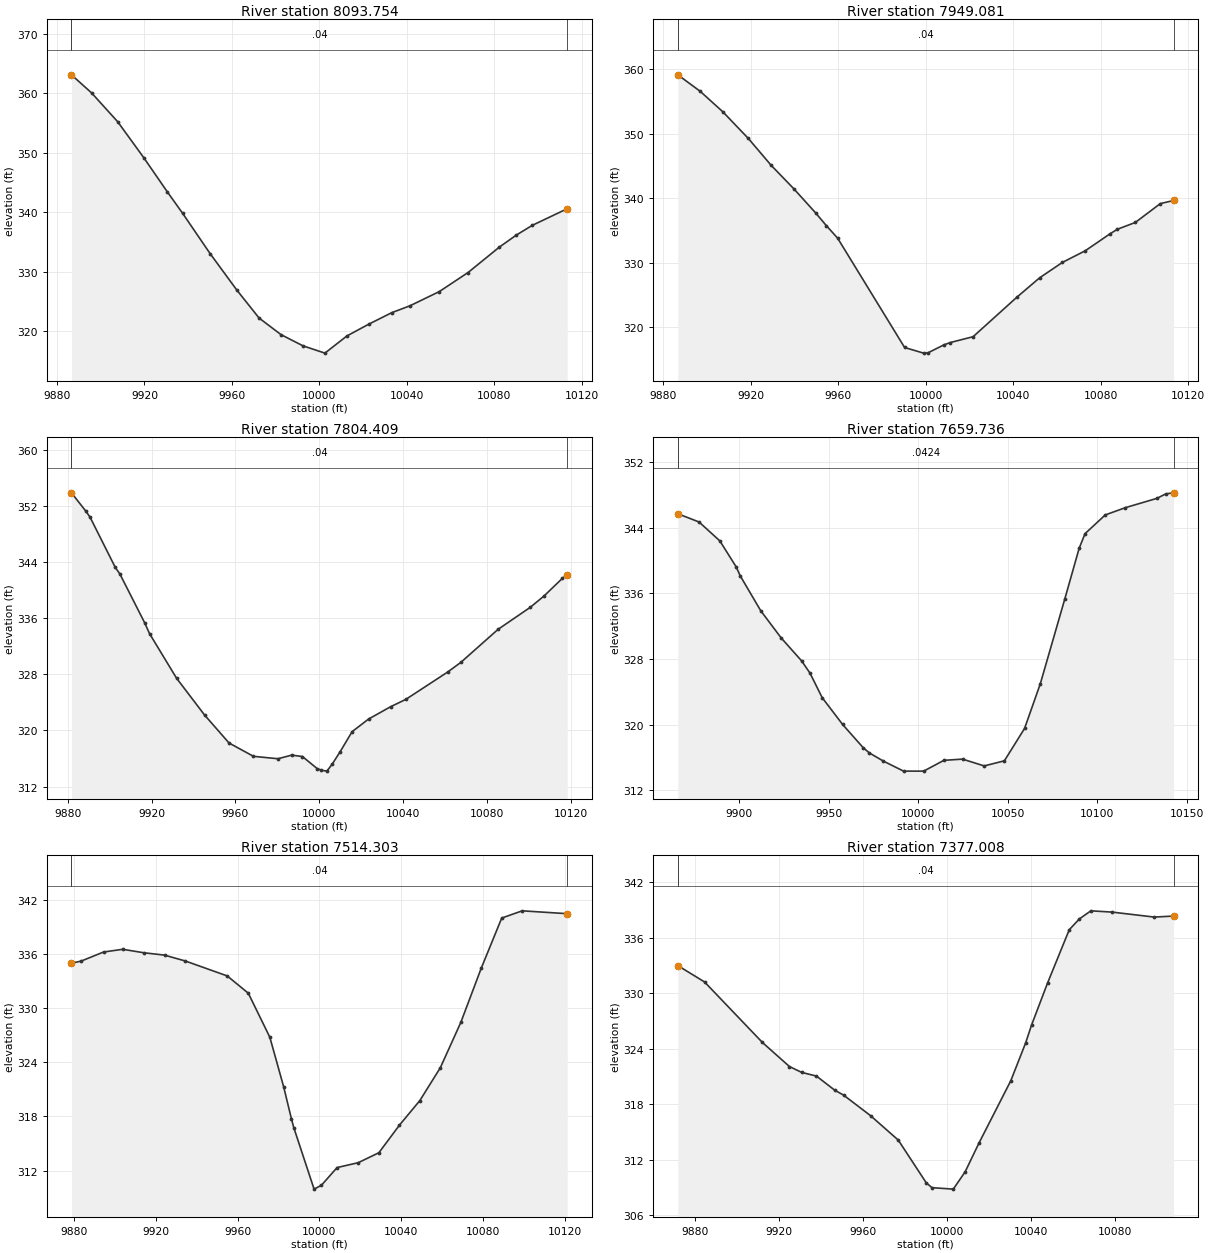
Type RM Length L Ch R = 1 ,8093.754,144.672500,144.672500,144.672500
XS GIS Cut Line= 6
824482.724337611784380.126911533824454.619965135784398.382069983
824426.976207846 784409.74622691824336.972246738784424.259742881
824311.549244394 784441.83735581824284.437117897784472.469438908
#Sta/Elev= 22
9886.593363.09489895.803360.05649907.728355.21939919.652 349.1779930.506343.3942
9937.511339.78359949.994333.05699962.218326.92469972.425322.20939982.479319.4146
9992.509317.537310002.54316.309810012.59 319.19410022.73321.201310033.12323.1108
10041.46324.268410054.86326.653910068.04329.863710082.36334.137710090.06336.1436
10097.45337.798710113.39340.5844
#Mann= 3 , 0 , 0
9886.593    0.04       09886.593    0.04       010113.39    0.04       0
#XS Ineff= 2 , 0
       0                               0
Bank Sta=9886.593,10113.39
Exp/Cntr=0.3,0.1

Type RM Length L Ch R = 1 ,7949.081,144.672500,144.672500,144.672500
XS GIS Cut Line= 6
824303.686581333784245.744371298824289.588414038784276.124361478
824283.541336249784309.845094229824299.998271288784398.728922054
824292.467810306784424.432262896 824272.51461774784460.287012354
#Sta/Elev= 24
9886.636359.12459896.839356.58179907.272353.38479918.888349.26449929.277345.1252
9939.585 341.5099949.628337.75139954.491335.78719959.678333.84289990.327316.8974
    9999316.025210000.83316.041510008.34 317.31310011.24 317.66810021.64318.5692
10041.74324.7126   10052327.676510062.42330.0651 10072.9331.874110084.35 334.529
10087.61335.208910095.79336.259510107.23339.181110113.29339.6629
#Mann= 3 , 0 , 0
9886.636    0.04       09886.636    0.04       010113.29    0.04       0
#XS Ineff= 2 , 0
       0                               0
Bank Sta=9886.636,10113.29
Exp/Cntr=0.3,0.1

Type RM Length L Ch R = 1 ,7804.409,144.672500,144.672500,144.672500
XS GIS Cut Line= 6
824271.243664136 784230.14959389824225.132160922784273.523109773
824169.712265064784306.928319486824150.136027095784321.236570218
824130.674910073784340.287663525824093.476527661784383.448210768
#Sta/Elev= 30
9881.746 353.9139888.577351.31159890.613350.4412 9902.66343.26739904.815342.3533
9916.743335.32649919.018333.81219931.903327.45279945.264322.20319956.931 318.211
9968.597316.30889980.264315.96659986.807316.4781 9991.93316.2833    9999 314.557
   10001314.324610003.61314.197410006.14315.188810009.82316.908110015.66319.8319
 10023.5321.629510034.07 323.39710041.25324.4316 10061.3328.348610067.52329.7151
10085.31334.436110100.63337.569710107.13339.167810115.95341.702110118.28342.1896
#Mann= 3 , 0 , 0
9881.746    0.04       09881.746    0.04       010118.28    0.04       0
#XS Ineff= 2 , 0
       0                               0
Bank Sta=9881.746,10118.28
Exp/Cntr=0.3,0.1

Type RM Length L Ch R = 1 ,7659.736,145.432700,145.432700,145.432700
XS GIS Cut Line= 3
824195.547048923784179.244645362824101.931354699784231.032050689
823951.121877757784309.282250976
#Sta/Elev= 30
9865.815345.67969877.705344.66969889.297342.37019898.364339.22529900.725338.0948
9912.153333.85649923.581330.54229935.009327.74549939.681326.25139946.437323.2798
9957.865320.00919969.294317.1931  9972.8316.54069980.609315.55079991.875314.3269
10003.14314.325810014.41  315.6410024.84315.787910036.94314.960610048.21 315.582
10059.47319.521210068.27324.9617   10082335.333610089.98341.481210093.27343.2574
10104.54345.5313 10115.8346.4205 10133.4347.552510138.33 348.095 10142.7348.2259
#Mann= 3 , 0 , 0
9865.815  0.0424       09865.815  0.0424       0 10142.7  0.0424       0
#XS Ineff= 2 , 0
       0                               0
Bank Sta=9865.815,10142.7
Exp/Cntr=0.3,0.1

Type RM Length L Ch R = 1 ,7514.303,137.295400,137.295400,137.295400
XS GIS Cut Line= 6
824229.554556638784091.814416373824147.313163155784108.848137891
824123.882589837784116.528798076824104.690668793784126.255730005
824092.322052648784129.388978731823993.007585637 784132.37170475
#Sta/Elev= 26
9878.833335.00649883.484335.2239 9894.54336.23879903.909 336.5399914.121336.1583
9924.333335.89269934.546335.2373 9954.97333.58399965.254331.67169975.778326.7892
9982.569321.26439986.301317.76549987.477316.7673 9997.41309.9379   10001310.3686
10008.66312.3308   10019312.870810029.09313.977210039.09317.0243 10049.1319.7627
 10059.1323.400710069.11328.425710079.11 334.44610089.11340.004110099.12340.8064
10121.12340.4896
#Mann= 3 , 0 , 0
9878.833    0.04       09878.833    0.04       010121.12    0.04       0
#XS Ineff= 2 , 0
       0                               0
Bank Sta=9878.833,10121.12
Exp/Cntr=0.3,0.1

Type RM Length L Ch R = 1 ,7377.008,153.570200,153.570200,153.570200
XS GIS Cut Line= 6
 824174.99989292784083.770208359 824155.46864292784065.324027807
824068.949180275783993.641993374824042.439673841783980.629574239
824013.849824846783973.346460775823975.839741349 783968.87110211
#Sta/Elev= 25
9871.598333.00249884.371331.23229911.969324.69219924.869322.09129930.634321.4638
 9937.77321.05729946.463319.5357 9950.67319.00839963.571 316.7799976.787314.1411
9990.129 309.5259992.861308.998610003.03308.840210008.69310.709810015.24313.7969
10030.45320.544310037.52324.623910040.37326.568810048.05331.138910058.36336.8749
10063.17338.044410068.68338.922810078.78338.786110098.92338.247210108.14338.3574
#Mann= 3 , 0 , 0
9871.598    0.04       09871.598    0.04       010108.14    0.04       0
#XS Ineff= 2 , 0
       0                               0
Bank Sta=9871.598,10108.14
Exp/Cntr=0.3,0.1

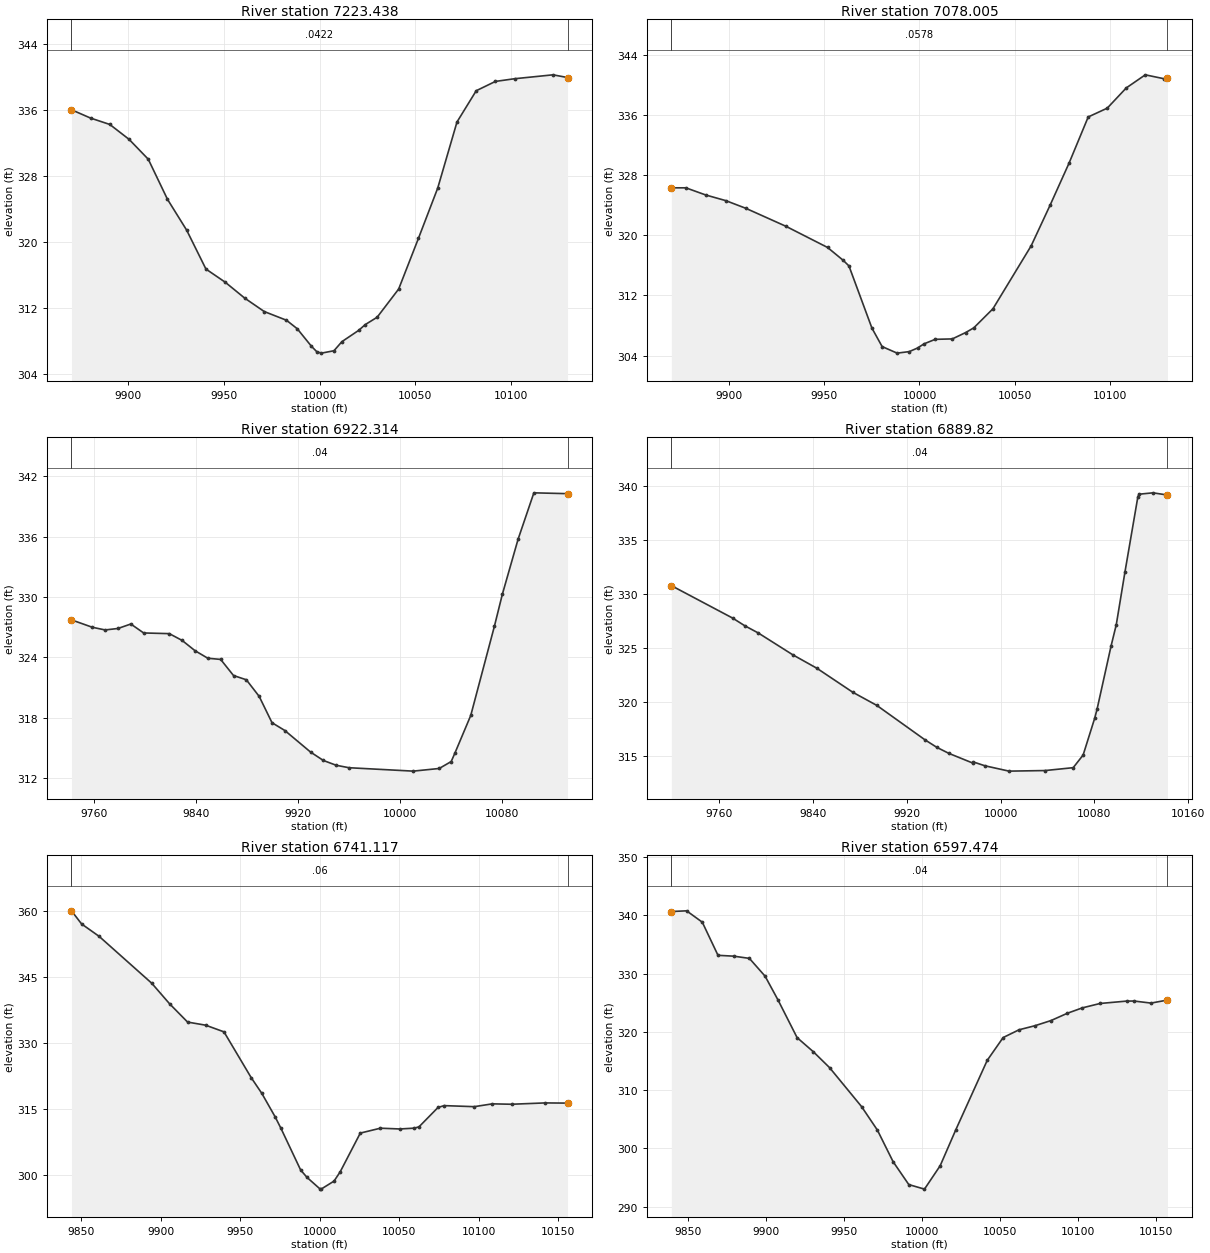
Type RM Length L Ch R = 1 ,7223.438,145.432700,145.432700,145.432700
XS GIS Cut Line= 6
824244.947091738783859.775614935824144.699159986783869.556380226
824130.780829779783878.935203005   824110.091148783907.595791708
824091.034876738783917.560500828824007.418858654783918.076663593
#Sta/Elev= 30
9870.624335.98829880.597334.97859890.623334.2075 9900.65332.40999910.676330.0006
9920.702325.14629930.728321.40499940.754316.7086 9950.81315.1158 9960.98313.1891
9971.151 311.5689982.739310.5149 9988.38309.48379995.731307.37529998.611306.6938
   10001306.534310007.52306.823210011.66307.922110020.36309.281910023.84309.9881
10030.03310.876610041.26  314.2910051.57320.421110061.63326.508910071.68 334.508
10081.71338.289310091.72339.417110101.73 339.74210121.75340.214110129.34339.8876
#Mann= 3 , 0 , 0
9870.624  0.0422       09870.624  0.0422       010129.34  0.0422       0
#XS Ineff= 2 , 0
       0                               0
Bank Sta=9870.624,10129.34
Exp/Cntr=0.3,0.1

Type RM Length L Ch R = 1 ,7078.005,155.690900,155.690900,155.690900
XS GIS Cut Line= 6
824252.278228414783732.654766897824197.776824263783749.889341406
824167.524439658 783763.42018291824117.453576162 783805.91593554
824095.627697053783808.679591299824013.356370781783808.445291943
#Sta/Elev= 29
9869.566326.3086  9877.2326.30749887.688325.35329898.176324.60629908.664323.5914
9929.769321.19819951.679318.38129959.868316.67839962.919315.92829975.007307.6579
9980.368305.20539988.246304.3381 9994.63304.5401    9999305.021510002.37305.5703
10008.25306.170710017.26306.228210024.28307.074910028.53307.695910038.61310.2338
10058.69 318.59510068.69324.021210078.69 329.63310088.69335.727410098.69336.8963
10108.69339.585210118.69341.325710128.69340.798310130.33340.8743
#Mann= 3 , 0 , 0
9869.566  0.0578       09869.566  0.0578       010130.33  0.0578       0
#XS Ineff= 2 , 0
       0                               0
Bank Sta=9869.566,10130.33
Exp/Cntr=0.3,0.1

Type RM Length L Ch R = 1 ,6922.314,32.494700,32.494700,32.494700
XS GIS Cut Line= 3
824341.231773019783693.649803594824056.154653013783658.605506048
 823973.64433974783718.851131603
#Sta/Elev= 30
9742.072327.72939758.426326.99359768.502326.72619778.577326.87269788.652327.3171
9798.727326.42719818.878326.35959828.953 325.6829839.029324.66449849.104323.9124
9859.179323.79519869.254322.1941 9879.33321.77089889.405320.1196 9899.48317.5003
9909.555 316.7249929.706314.58399939.781313.74599949.857313.26779959.932 313.023
10010.31312.684810030.73 312.94810040.14313.639610043.11314.500710055.49318.2269
10074.06327.105110080.25  330.2610092.63335.749310105.02340.364510131.46340.2805
#Mann= 3 , 0 , 0
9742.072    0.04       09742.072    0.04       010131.46    0.04       0
#XS Ineff= 2 , 0
       0                10021.94       0
Bank Sta=9742.072,10131.46
Exp/Cntr=0.3,0.1

Type RM Length L Ch R = 1 , 6889.82,148.702200,148.702200,148.702200
XS GIS Cut Line= 4
824356.073093235783568.891911492824126.877778649783619.969724447
824025.376996487783642.889255926823954.653870851 783688.72831884
#Sta/Elev= 27
9719.112330.78899771.438327.78189781.684 327.0799793.166326.41249822.665324.3895
9843.156323.14789873.892320.91969894.382319.70399935.364316.52579945.609315.8194
9955.855315.26439976.359 314.3629976.768 314.4689986.611314.115710007.11 313.622
10037.87 313.67510061.87313.941510070.35315.109910080.25 318.52710082.27319.3679
10094.19325.200310098.64327.1778 10106.1 332.09510117.03338.996610118.02339.2477
10129.94339.376110142.27339.1735
#Mann= 3 , 0 , 0
9719.112    0.04       09719.112    0.04       010142.27    0.04       0
#XS Ineff= 2 , 0
       0                10020.87       0
Bank Sta=9719.112,10142.27
Exp/Cntr=0.3,0.1

Type RM Length L Ch R = 1 ,6741.117,143.643100,143.643100,143.643100
XS GIS Cut Line= 6
824200.765582967783412.977416101824118.333987898783453.613323501
824087.969555183783473.112897616824006.531587334783532.323100716
823968.073752479783553.314675891823932.107442779783569.347815606
#Sta/Elev= 30
9844.013 360.037 9850.37357.05239861.396354.22829894.474 343.564 9905.68338.8885
9917.033334.71369928.386334.00529939.916332.48679957.026 322.0679963.685318.4993
 9972.04313.17529975.724 310.541 9988.13 301.0429992.126  299.3610000.41296.6956
   10001296.686910009.13298.515110012.99300.619710025.64309.4431 10038.3310.5575
10050.51310.381510059.69310.570410062.57310.872310074.53315.278610078.37315.6945
10097.31315.457910108.71316.099710120.74316.007510141.86316.310810155.98316.2662
#Mann= 3 , 0 , 0
9844.013    0.06       09844.013    0.06       010155.98    0.06       0
#XS Ineff= 2 , 0
       0                               0
Bank Sta=9844.013,10155.98
Exp/Cntr=0.3,0.1

Type RM Length L Ch R = 1 ,6597.474,46.678000,46.678000,46.678000
XS GIS Cut Line= 6
824134.715741307783362.692241207824066.750782877783369.480777144
824026.159248531783380.863764957823935.603585035 783390.91339989
823898.215992659783398.084321558823825.347739637783425.338697284
#Sta/Elev= 30
9839.516340.6834 9849.28340.80269859.329338.84989869.379333.16149879.429333.0151
9889.479332.63429899.528329.57799907.819325.48069920.023 319.0219930.409316.5981
9940.794313.87129961.292307.17489971.433303.13469981.493297.70669991.528293.7794
10001.57292.996810011.61297.009610021.66303.211410041.75315.120310051.94319.0351
10062.12320.3692 10072.3321.066910082.58321.953610093.04323.205710102.59324.1296
10113.98324.886610131.07325.298410135.71325.3069 10146.6324.955310157.12 325.474
#Mann= 3 , 0 , 0
9839.516    0.04       09839.516    0.04       010157.12    0.04       0
#XS Ineff= 2 , 0
       0                               0
Bank Sta=9839.516,10157.12
Exp/Cntr=0.3,0.1

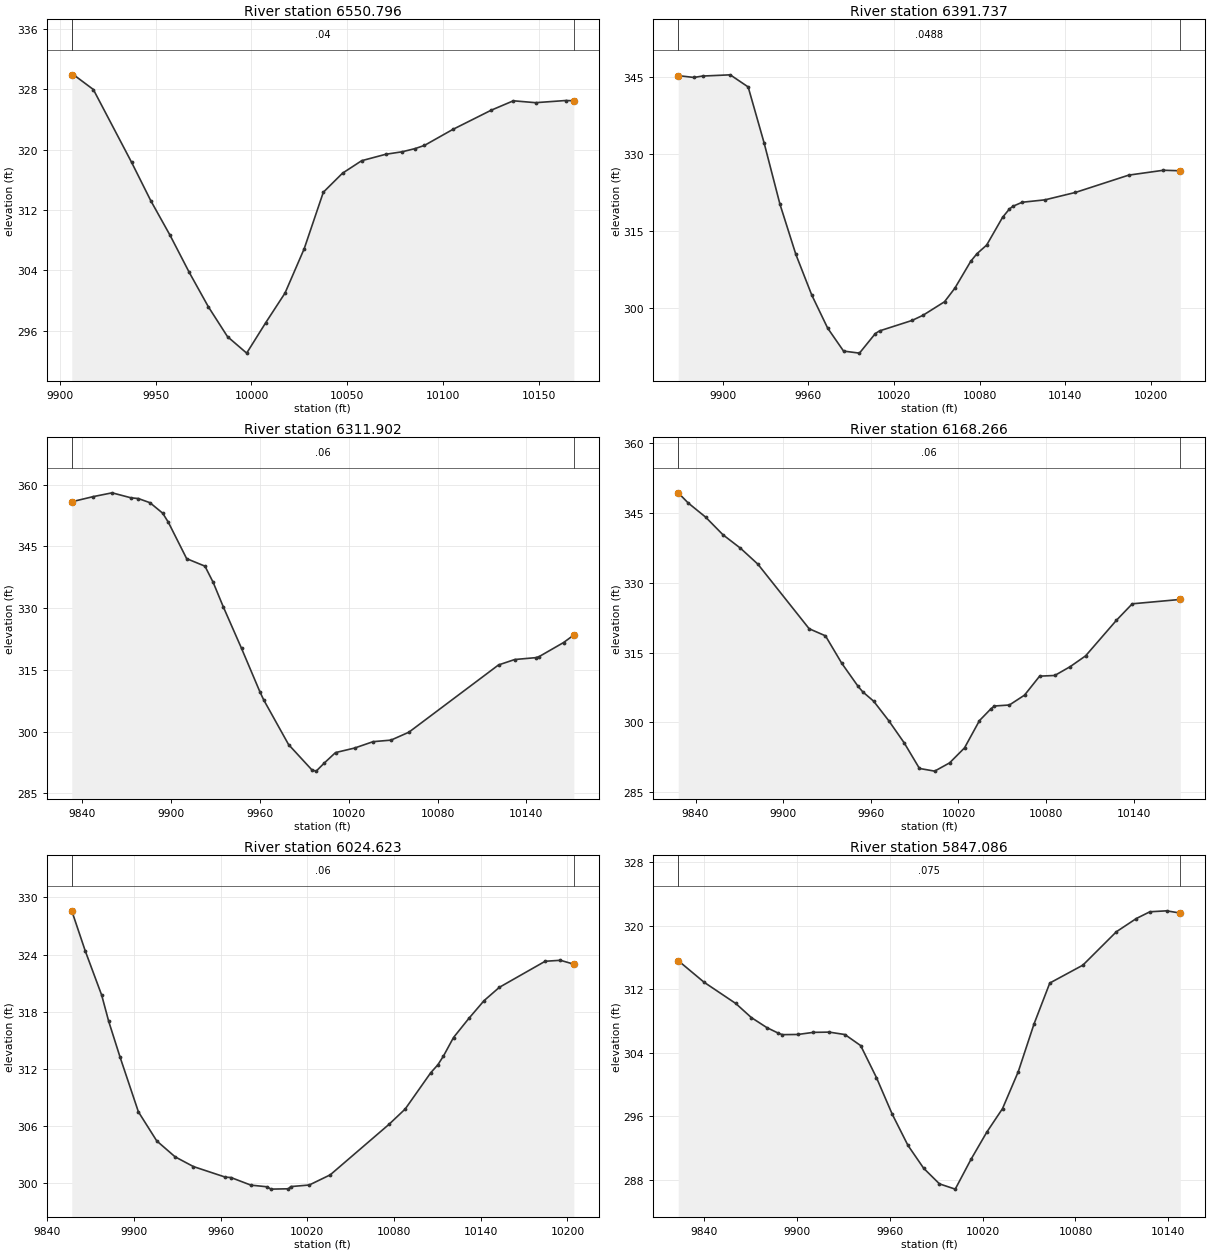
Type RM Length L Ch R = 1 ,6550.796,159.059100,159.059100,159.059100
XS GIS Cut Line= 3
824076.258573443783345.922986135823912.413087338783337.242430583
823827.777670711 783387.15562503
#Sta/Elev= 26
9906.109329.9175 9907.37329.86759917.384327.97129937.412 318.2919947.426313.2075
 9957.44 308.6499967.454303.73439977.468299.15839987.482295.19439997.496293.0091
10007.51297.068310017.52300.969810027.54306.846810037.55314.348310047.57316.8728
10057.58318.528810070.18319.382210078.79319.714910085.46320.1315 10090.4320.5589
10105.14322.667310125.23325.222410136.84326.473510148.45326.2241 10164.2326.5109
10168.44326.4799
#Mann= 3 , 0 , 0
9906.109    0.04       09906.109    0.04       010168.44    0.04       0
#XS Ineff= 2 , 0
       0                               0
Bank Sta=9906.109,10168.44
Exp/Cntr=0.3,0.1

Type RM Length L Ch R = 1 ,6391.737,79.835500,79.835500,79.835500
XS GIS Cut Line= 4
824015.494684607783096.357013911823985.860464573783134.169285998
823903.923997909783301.528877541823804.991212368783364.369166687
#Sta/Elev= 30
9868.875345.22749879.856344.87879885.888345.14989905.266345.39049917.841343.0321
9928.975332.15319940.109320.16829951.243310.38919962.377302.46399973.512296.0182
9984.646 291.542 9995.78291.144510006.91294.965110009.84295.477910032.58297.5114
10040.32298.527910055.33301.156310062.58303.804410073.72 309.04910078.07310.5275
10084.85312.205310095.99  317.6110100.81319.252410103.26319.769810109.73320.5535
10125.68321.022110147.03322.467710184.33325.8396 10208.6326.788210220.46 326.691
#Mann= 3 , 0 , 0
9868.875  0.0488       09868.875  0.0488       010220.46  0.0488       0
#XS Ineff= 2 , 0
       0                               0
Bank Sta=9868.875,10220.46
Exp/Cntr=0.3,0.1

Type RM Length L Ch R = 1 ,6311.902,143.635700,143.635700,143.635700
XS GIS Cut Line= 6
823982.970867247783033.694049112823948.914031876783076.508715826
823896.885232762783148.294938002823862.182544379783190.631355123
823812.850690494783263.426074086823780.785425441783305.401915026
#Sta/Elev= 30
9833.112 355.8199847.558 357.0699860.336357.99159873.114356.77779878.043356.6029
9885.892355.58989894.489353.04369898.307350.83049910.657341.99779923.007340.1765
 9928.57336.21939935.357330.31359947.708320.18579960.058309.6755 9962.65307.6843
9979.451296.82399995.223 290.656 9998.08290.372310003.55 292.34210011.12 294.877
10023.98295.9786 10036.5297.530710048.58297.907410060.66299.831810121.14316.1694
 10132.1  317.4910146.31317.943510148.57318.202810165.04321.612210171.99323.4488
#Mann= 3 , 0 , 0
9833.112    0.06       09833.112    0.06       010171.99    0.06       0
#XS Ineff= 2 , 0
       0                               0
Bank Sta=9833.112,10171.99
Exp/Cntr=0.3,0.1

Type RM Length L Ch R = 1 ,6168.266,143.643000,143.643000,143.643000
XS GIS Cut Line= 6
823831.300426751782959.330816663823788.063380223783025.651995518
823766.951944306783067.854665063 823753.48283853783112.335189247
823733.532822079783196.843636023823703.661050101783275.367421759
#Sta/Elev= 30
9828.164349.31939834.931347.15449846.868344.11349858.806340.30459870.743 337.429
9882.681333.99879917.786320.12519928.968318.59559940.149312.6891 9951.33307.7297
9954.522306.55599961.983304.54749972.425300.30849982.866295.60579993.308290.1041
10003.72289.528810013.94291.298610024.16294.517610034.39300.378810042.05302.8553
10044.61303.519210054.89303.735710065.24305.8513 10075.6309.933110085.95310.0809
10096.48311.967510107.05314.284810128.17321.932810139.03325.476810171.92326.4137
#Mann= 3 , 0 , 0
9828.164    0.06       09828.164    0.06       010171.92    0.06       0
#XS Ineff= 2 , 0
       0                               0
Bank Sta=9828.164,10171.92
Exp/Cntr=0.3,0.1

Type RM Length L Ch R = 1 ,6024.623,177.537100,177.537100,177.537100
XS GIS Cut Line= 5
823761.296692818782939.222731531823679.615497828 783003.22665295
823603.420353293783075.764430583 823580.86659047783118.433711514
823551.607654989783203.772273421
#Sta/Elev= 30
9856.966328.59849866.333324.3737 9877.67319.74719882.546  316.999890.375313.2515
9903.079307.50379915.783304.45329928.488302.78299941.192301.75989963.309  300.65
9967.109300.61319980.916299.81439992.315299.63779994.723299.394510006.82299.4296
10008.53299.662110021.32299.827610035.82300.892110076.39306.1769 10087.7307.7992
10105.36311.603510110.32312.4432 10114.2313.364910121.14315.303310131.71317.3006
10142.29319.173910152.86320.569910184.57323.305310195.14323.407710204.42322.9973
#Mann= 3 , 0 , 0
9856.966    0.06       09856.966    0.06       010204.42    0.06       0
#XS Ineff= 2 , 0
       0                               0
Bank Sta=9856.966,10204.42
Exp/Cntr=0.3,0.1

Type RM Length L Ch R = 1 ,5847.086,112.257800,112.257800,112.257800
XS GIS Cut Line= 6
823524.156711701782868.696824988823516.480683514782903.976091159
823514.380205202782932.360786562823515.974800021 782956.00088145
823544.574545711783109.377847239823514.192601234783183.162569478
#Sta/Elev= 30
9823.597315.58239840.281312.86679860.728310.19119870.756308.42179880.783307.1546
9888.164306.45459890.809306.26529900.832 306.2889910.854 306.5549921.012306.5843
9931.184306.27899941.357304.88619951.529300.86239961.701296.25549971.874292.3195
9982.046289.42879992.218 287.47110002.39286.809410012.56290.559710022.74293.9798
10032.91296.950710043.08301.604810053.25307.612810063.42312.764510084.77315.0176
 10106.4319.224910119.29320.892110128.03321.740310138.85321.859510147.67321.5751
#Mann= 3 , 0 , 0
9823.597   0.075       09823.597   0.075       010147.67   0.075       0
#XS Ineff= 2 , 0
       0                               0
Bank Sta=9823.597,10147.67
Exp/Cntr=0.3,0.1

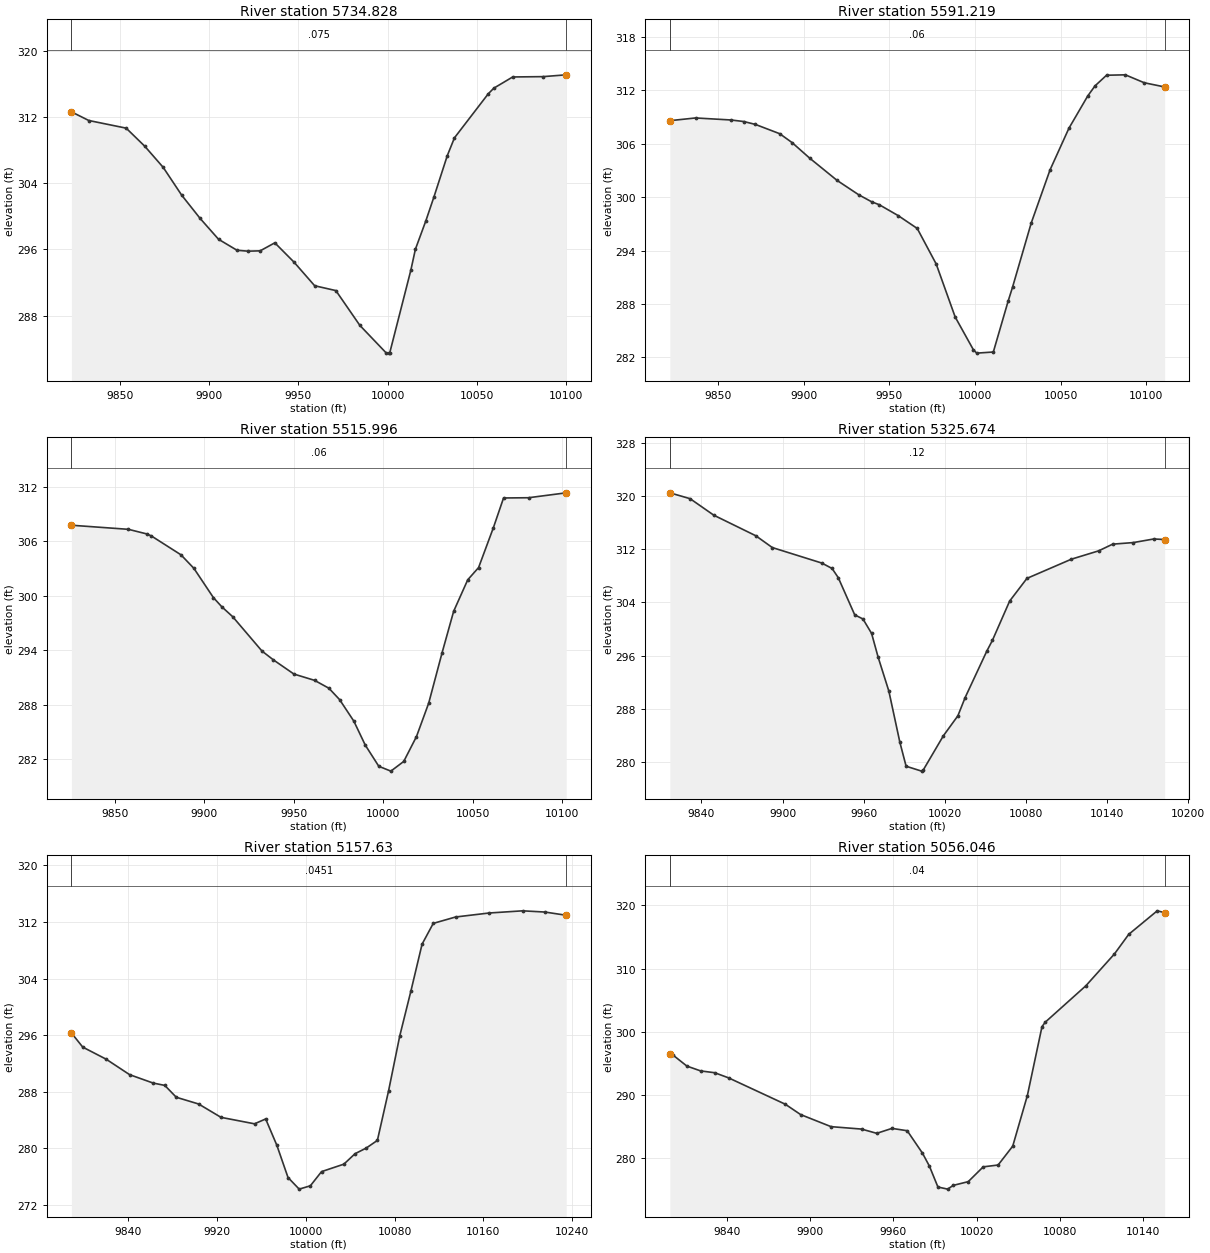
Type RM Length L Ch R = 1 ,5734.828,143.609100,143.609100,143.609100
XS GIS Cut Line= 6
 823494.03489882782875.695078981823457.285020852782997.400173556
823443.190197753783019.357121645823410.940537085783051.058829386
823397.544344656783074.644170392823381.422183721783123.543038424
#Sta/Elev= 30
9822.803312.64499832.547311.59499853.491310.66989863.926308.47749874.256 305.918
9884.587302.56349894.917299.74879905.247297.22459915.578295.89719921.727295.7854
 9928.56295.82659936.776296.7961 9947.49294.46929959.092291.60419970.975291.0174
9984.417286.8091 9999.06283.4998   10001283.451610001.12283.454510012.98 293.484
10015.54296.024610021.39299.455310025.92302.344710033.42307.351810037.42309.4988
10056.34  314.8210059.47315.504710070.04316.8618 10087.1316.901610100.02317.1204
#Mann= 3 , 0 , 0
9822.803   0.075       09822.803   0.075       010100.02   0.075       0
#XS Ineff= 2 , 0
       0                               0
Bank Sta=9822.803,10100.02
Exp/Cntr=0.3,0.1

Type RM Length L Ch R = 1 ,5591.219,75.223300,75.223300,75.223300
XS GIS Cut Line= 6
823410.176290137782864.345411091 823352.66151043782922.322730841
823330.623328675782950.982081888 823305.18282068783004.539658291
823296.086048569783022.715380372823258.131349514783105.848520553
#Sta/Elev= 30
9821.888308.59879836.896308.90419857.636308.67549865.068308.50219871.836308.1768
9886.035307.1325 9893.24306.13569903.554304.38149919.546 301.8819932.161300.2692
9939.707299.48159944.155299.15219955.226297.92529966.297 296.4879977.368292.4919
9988.439286.5393    9999282.8807   10001282.478610010.71282.603110019.33288.3008
10021.94289.896110032.83297.095410043.82303.068510054.82307.741410065.81311.3708
 10070.1312.5148 10076.8313.704310087.79313.750410098.79312.861210110.71312.3885
#Mann= 3 , 0 , 0
9821.888    0.06       09821.888    0.06       010110.71    0.06       0
#XS Ineff= 2 , 0
       0                               0
Bank Sta=9821.888,10110.71
Exp/Cntr=0.3,0.1

Type RM Length L Ch R = 1 ,5515.996,190.322000,190.322000,190.322000
XS GIS Cut Line= 6
823389.313474353782857.368692862823357.134497722782884.739424183
823334.259716153782899.379833329 823311.55153474782908.763824377
823274.005407012782930.049151094823176.584521449783030.103033544
#Sta/Elev= 30
9825.606307.74019857.525307.28829867.851306.77829870.385306.55379886.884304.4848
 9894.13302.99239905.029299.77469909.725298.76249915.849297.66489932.225293.8855
9938.606292.91399950.101291.35239961.597 290.663 9969.65289.79439975.649288.5373
9983.607286.16849989.983283.53639997.565281.198610004.32280.666310011.52281.7346
10018.65284.476510025.48288.153810032.99293.716210039.44298.266310047.32301.7336
10053.39303.078610061.66307.466610067.35310.740910081.31310.767210102.39311.3075
#Mann= 3 , 0 , 0
9825.606    0.06       09825.606    0.06       010102.39    0.06       0
#XS Ineff= 2 , 0
       0                               0
Bank Sta=9825.606,10102.39
Exp/Cntr=0.3,0.1

Type RM Length L Ch R = 1 ,5325.674,168.043300,168.043300,168.043300
XS GIS Cut Line= 4
823353.566285647782662.836002807823271.943381525782780.004365171
823196.244720466782875.450503076823129.761548585782951.807413364
#Sta/Elev= 30
9816.646320.50389831.632319.62129849.127 317.138 9880.22314.03759892.407312.2617
9928.969309.9302  9936.6309.11429941.156307.73639953.343302.12789959.442301.5036
9965.818 299.3359970.616 295.7829978.582 290.6499986.709282.95959991.345279.3315
 10002.8278.593510004.11278.794210018.89283.912810029.63286.926510034.99289.6728
10051.08296.695610055.16298.283510067.92304.207610080.69 307.61910113.62310.5153
 10133.7311.765810144.07312.7737 10159.3313.011510174.53313.555510182.51313.4712
#Mann= 3 , 0 , 0
9816.646    0.12       09816.646    0.12       010182.51    0.12       0
#XS Ineff= 2 , 0
       0                               0
Bank Sta=9816.646,10182.51
Exp/Cntr=0.3,0.1

Type RM Length L Ch R = 1 , 5157.63,101.584700,101.584700,101.584700
XS GIS Cut Line= 3
 823046.08874484782575.331546116 823075.00000003782661.568618119
823111.663361192783014.003117606
#Sta/Elev= 30
9789.183296.31019799.381294.30549820.475292.59439841.569290.40589862.663289.2225
 9873.21288.88589883.588287.20829903.696286.25459923.804284.36789953.965283.4518
9964.019 284.1399974.073280.41599984.127275.85389994.181274.210910004.24274.6834
10014.29276.6863 10034.4277.745310044.45279.221910054.51280.020110064.56 281.106
10074.61288.109810084.67295.878910094.72302.236610104.77 308.86810114.83311.8097
10134.94312.7138 10165.1313.278810195.26313.586510215.37313.414210234.47312.9594
#Mann= 3 , 0 , 0
9789.183  0.0451       09789.183  0.0451       010234.47  0.0451       0
#XS Ineff= 2 , 0
       0                               0
Bank Sta=9789.183,10234.47
Exp/Cntr=0.3,0.1

Type RM Length L Ch R = 1 ,5056.046,246.249600,246.249600,246.249600
XS GIS Cut Line= 6
823042.108133435782572.733449757823042.108133435782645.650116444
822988.449223689782763.117124105822976.868360184782791.526688707
822955.258543862782856.527528501822942.774540185782910.198945991
#Sta/Elev= 30
9798.934 296.4399801.201296.33099811.201294.58729821.201293.81949831.201293.5401
9841.201292.7289 9882.11288.55429893.082286.92499915.026285.0115 9936.97284.6276
9947.942 283.9569958.914284.73719969.886284.36619980.891280.81589985.875278.7657
9992.003 275.467    9999275.132310003.03275.725810013.83276.314110024.63278.6556
10035.34278.943510045.88281.929410056.42289.931610066.95300.8213 10069.3301.5315
10098.57307.291610119.14 312.32410129.41315.416510149.94 319.13810155.28318.8507
#Mann= 3 , 0 , 0
9798.934    0.04       09798.934    0.04       010155.28    0.04       0
#XS Ineff= 2 , 0
       0                               0
Bank Sta=9798.934,10155.28
Exp/Cntr=0.3,0.1