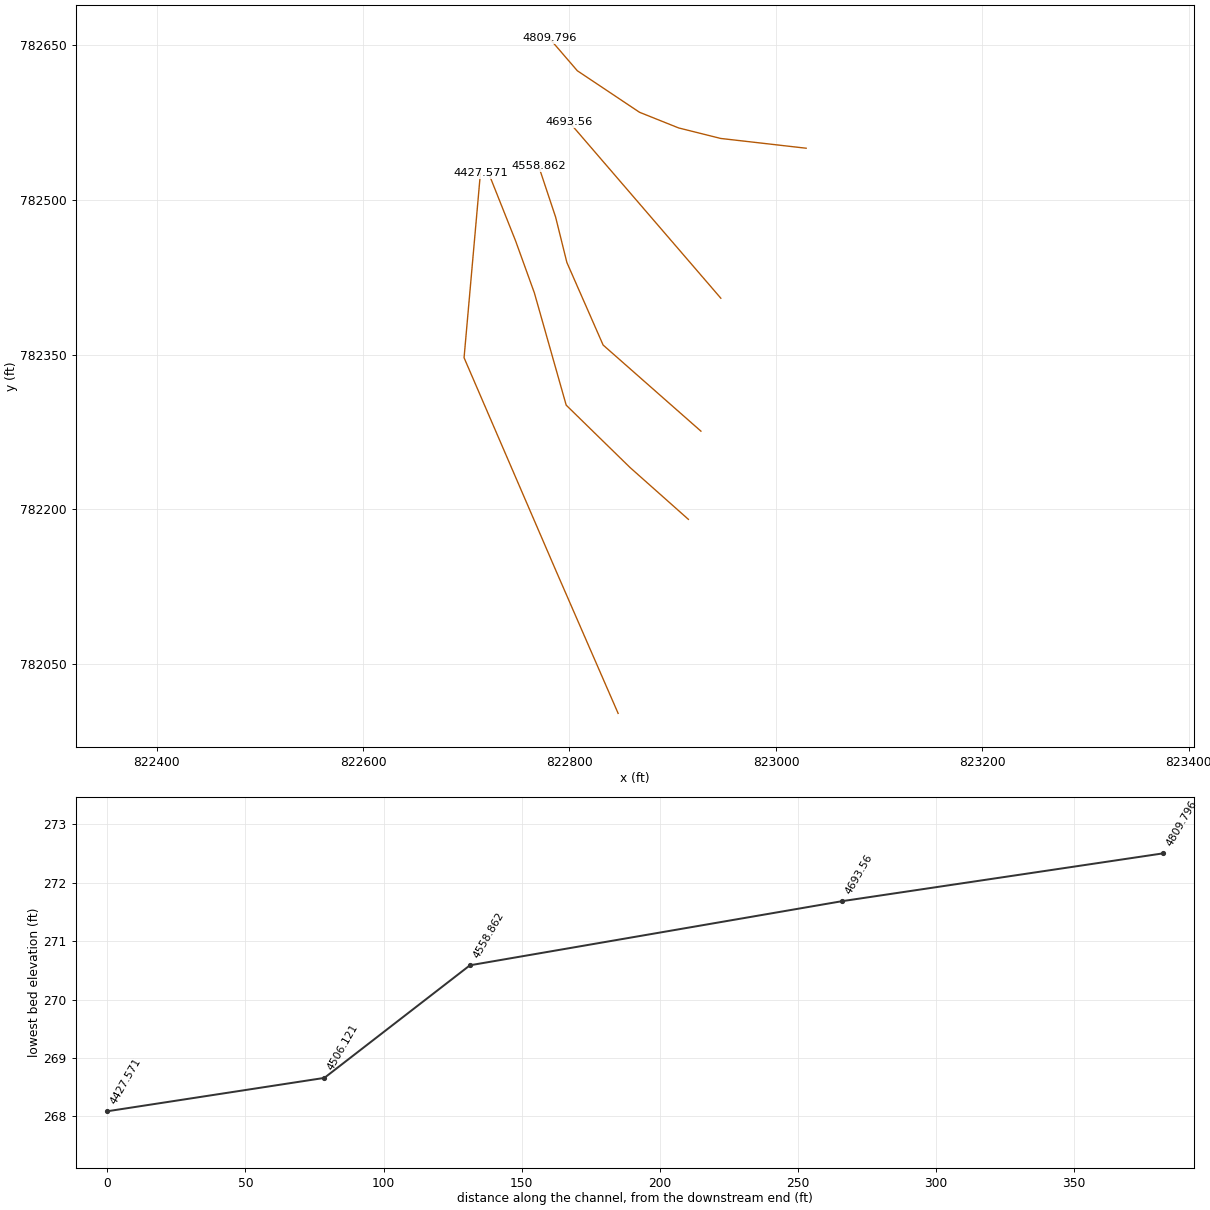
HEC-RAS study 17386_ras.prj: 17386

--- 17386_ras.g01 (geometry) --- (continued)

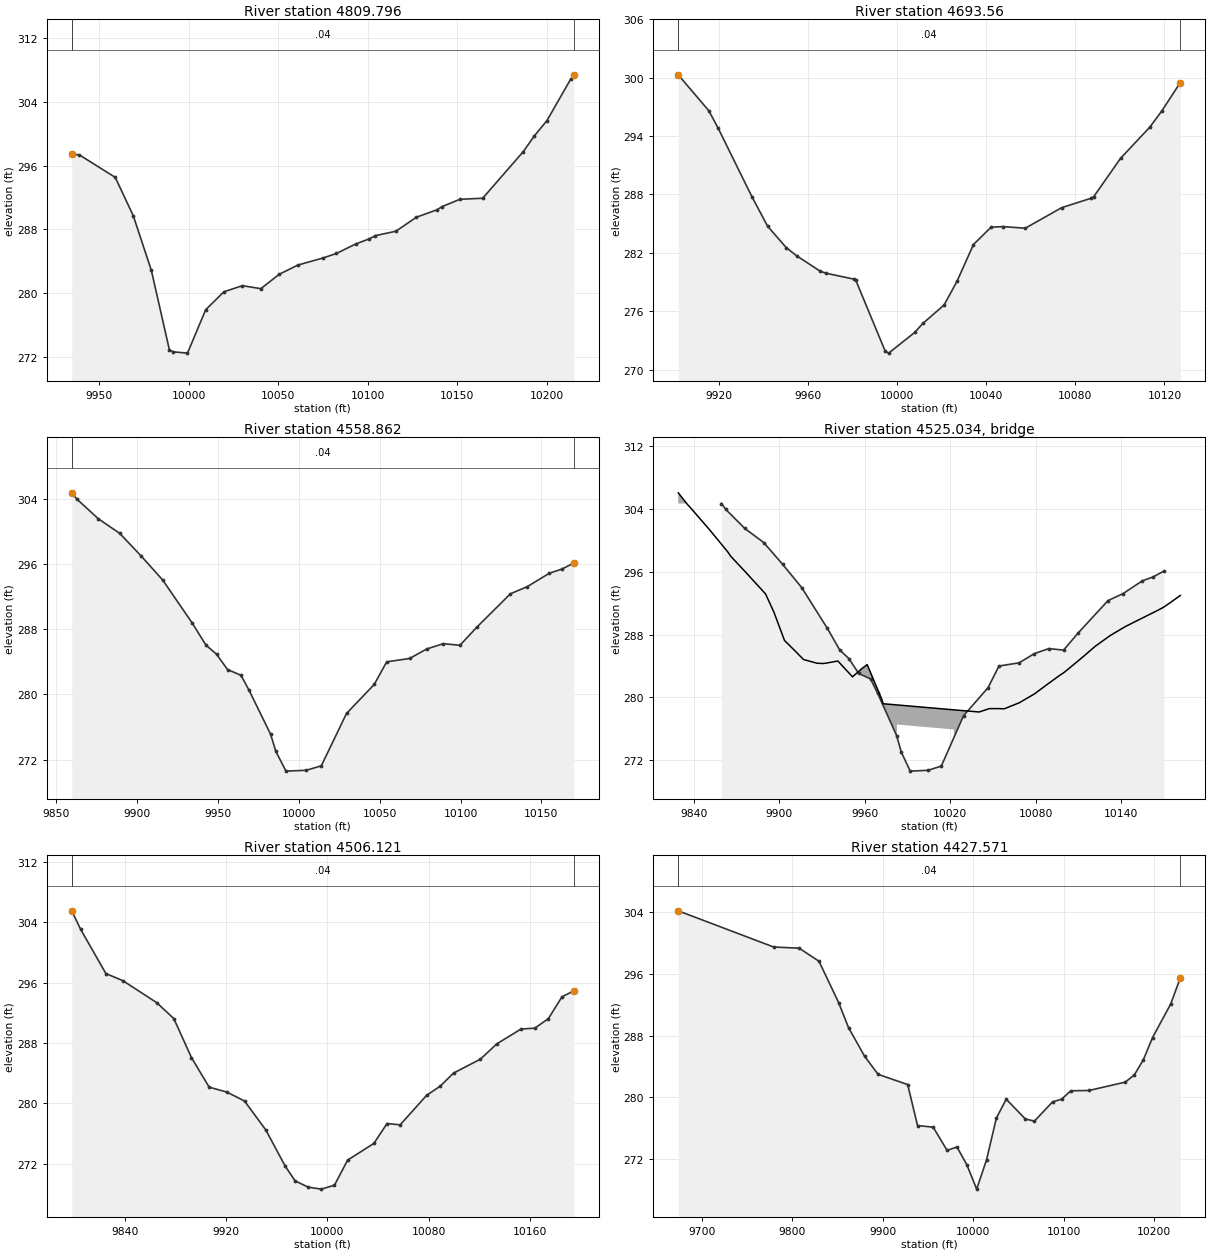
Type RM Length L Ch R = 1 ,4809.796,116.235600,116.235600,116.235600
XS GIS Cut Line= 6
823029.246601608782549.905879694822946.486650221782559.373289094
822905.669104383782569.582518567822867.863736086 782584.71519764
822807.587190281782624.957469564822780.524907609782656.359787183
#Sta/Elev= 30
9934.756297.43169939.003297.3461 9959.04294.52789969.123 289.7079979.207282.8606
9989.291272.89729991.359272.66529999.378272.503110009.54277.939810019.72280.1894
10030.03280.957610040.34280.580610050.64282.384810060.98283.536210074.84284.4135
10082.53284.9902 10093.3286.176610100.98 286.83310104.27287.225510115.75 287.778
10127.24289.537810138.75290.467310141.46 290.85810151.49291.778210164.23291.9134
10186.93297.764310192.96299.690410200.13301.647810213.33306.821910215.13307.3784
#Mann= 3 , 0 , 0
9934.756    0.04       09934.756    0.04       010215.13    0.04       0
#XS Ineff= 2 , 0
       0                               0
Bank Sta=9934.756,10215.13
Exp/Cntr=0.3,0.1

Type RM Length L Ch R = 1 , 4693.56,134.698200,134.698200,134.698200
XS GIS Cut Line= 2
822946.596223474782404.611424223822799.618635088782575.331546128
#Sta/Elev= 28
9901.845300.28349915.554296.59639919.619294.86439934.946287.73919941.945284.7304
9950.273282.5347 9955.14281.6602  9965.6280.09679968.335279.88499980.927279.2757
9981.531 279.1649994.726271.87259996.254271.684110007.92273.804610011.58 274.732
10021.12276.627210026.91279.058710034.31 282.84710042.24284.628510047.51284.6863
10057.56284.5217 10073.9286.632610087.09287.600710088.22287.745110100.29 291.698
10113.49294.921810118.87296.591410127.12299.4879
#Mann= 3 , 0 , 0
9901.845    0.04       09901.845    0.04       010127.12    0.04       0
#XS Ineff= 2 , 0
       0                               0
Bank Sta=9901.845,10127.12
Exp/Cntr=0.3,0.1

Type RM Length L Ch R = 1 ,4558.862,52.741200,52.741200,52.741200
XS GIS Cut Line= 5
822927.310337543782275.840506524822832.577963084782359.239866897
822797.461823672782439.214250535822786.553960145782483.205481052
822770.227392226782532.232650205
#Sta/Elev= 30
9859.485304.71529862.563303.96239875.886301.53659889.209299.73369902.532296.9404
9915.855293.9905 9933.88288.77839942.501286.04019949.014284.92749955.824283.0421
9964.147 282.3419969.147280.50569982.471275.10859985.697 273.0169991.988270.5864
10004.55270.690510013.83 271.23910029.42277.6558 10046.6281.226510054.29283.9908
10068.44284.3989   10079 285.56510089.31286.214910099.61286.018510109.91288.2174
 10130.8292.333610141.34293.222510154.93294.860510162.42295.350910170.04296.1015
#Mann= 3 , 0 , 0
9859.485    0.04       09859.485    0.04       010170.04    0.04       0
#XS Ineff= 2 , 0
       0                               0
Bank Sta=9859.485,10170.04
Exp/Cntr=0.3,0.1

Type RM Length L Ch R = 3 ,4525.034,,,
BEGIN DESCRIPTION:
END DESCRIPTION:
Bridge Culvert--1,0,-1,-1, 0
Deck Dist Width WeirC Skew NumUp NumDn MinLoCord MaxHiCord MaxSubmerge Is_Ogee
16.370600,20.000000,2.6,0, 48, 48, , , 0.95, 0, 0,0,,
 9829.17 9835.71 9837.14 9850.46 9850.84 9863.79 9865.97 9877.11 9881.10 9890.44
 9896.23 9903.76 9911.36 9917.09 9926.49 9930.41 9932.69 9941.21 9951.50 9958.05
 9961.78 9972.06 9973.00 9982.66 9982.6610022.6610022.6610040.4210047.5310053.13
10058.0610068.6010079.1310084.9210089.6710096.9110100.2610110.9810114.1810121.70
10132.4310141.9110143.1510153.8710164.5910169.6410175.3110181.55
  306.08  304.58  304.31  301.52  301.44  298.58  298.00  295.84  295.04  293.19
  290.90  287.25  285.88  284.82  284.35  284.31  284.35  284.63  282.61  283.66
  284.17  279.74  279.18  279.03  279.03  278.40  278.40  278.13  278.56  278.56
  278.54  279.31  280.43  281.21  281.85  282.80  283.21  284.82  285.31  286.49
  287.89  288.91  289.04  290.02  290.99  291.47  292.18  292.99
 -693.92 -695.42 -695.69 -698.48 -698.56 -701.42 -702.00 -704.16 -704.96 -706.81
 -709.10 -712.75 -714.12 -715.18 -715.65 -715.69 -715.65 -715.37 -717.39 -716.34
 -715.83 -720.26 -720.82 -720.97  276.53  275.90 -721.60 -721.87 -721.44 -721.44
 -721.46 -720.69 -719.57 -718.79 -718.15 -717.20 -716.79 -715.18 -714.69 -713.51
 -712.11 -711.09 -710.96 -709.98 -709.01 -708.53 -707.82 -707.01
 9829.17 9835.71 9837.14 9850.46 9850.84 9863.79 9865.97 9877.11 9881.10 9890.44
 9896.23 9903.76 9911.36 9917.09 9926.49 9930.41 9932.69 9941.21 9951.50 9958.05
 9961.78 9972.06 9973.00 9975.58 9975.5810015.5810015.5810040.4210047.5310053.13
10058.0610068.6010079.1310084.9210089.6710096.9110100.2610110.9810114.1810121.70
10132.4310141.9110143.1510153.8710164.5910169.6410175.3110181.55
  306.08  304.58  304.31  301.52  301.44  298.58  298.00  295.84  295.04  293.19
  290.90  287.25  285.88  284.82  284.35  284.31  284.35  284.63  282.61  283.66
  284.17  279.74  279.18  279.14  279.14  278.52  278.52  278.13  278.56  278.56
  278.54  279.31  280.43  281.21  281.85  282.80  283.21  284.82  285.31  286.49
  287.89  288.91  289.04  290.02  290.99  291.47  292.18  292.99
 -693.92 -695.42 -695.69 -698.48 -698.56 -701.42 -702.00 -704.16 -704.96 -706.81
 -709.10 -712.75 -714.12 -715.18 -715.65 -715.69 -715.65 -715.37 -717.39 -716.34
 -715.83 -720.26 -720.82 -720.86  276.64  276.02 -721.48 -721.87 -721.44 -721.44
 -721.46 -720.69 -719.57 -718.79 -718.15 -717.20 -716.79 -715.18 -714.69 -713.51
 -712.11 -711.09 -710.96 -709.98 -709.01 -708.53 -707.82 -707.01
BR Coef=-1 , 0 , 0 ,, 0 ,,,0.8,0,1,0,
WSPro=,,,, 1 ,,,, 0 ,,,, 0 ,,,,-1 ,-1 ,-1 , 0 , 0 , 0 , 0 , 0
BC Design=,, 0 ,, 0 ,,,,,,

Type RM Length L Ch R = 1 ,4506.121,78.550200,78.550200,78.550200
XS GIS Cut Line= 6
822915.172852993782190.396335781822858.622261375782240.634292424
822796.800704032 782301.01254487822765.998152792782409.693244457
822747.871127635 782459.89116028 822722.46451965782523.729669094
#Sta/Elev= 30
9797.783305.49769804.715 303.0729824.766297.19369838.143296.25899864.895  293.35
9878.489291.23839892.467286.06339906.445282.15939920.423281.50299934.401280.3265
9951.235276.49599966.444 271.7469974.379269.75599984.772268.92019995.166268.6571
10005.56269.181610015.95272.494810036.74274.712710047.14277.342210057.53277.1703
10078.44281.076110089.08 282.27410099.71284.013310120.97285.863910133.94287.8862
 10153.2289.860310163.96289.956410174.72291.221210185.48  294.1110194.88294.9055
#Mann= 3 , 0 , 0
9797.783    0.04       09797.783    0.04       010194.88    0.04       0
#XS Ineff= 2 , 0
       0                               0
Bank Sta=9797.783,10194.88
Exp/Cntr=0.3,0.1

Type RM Length L Ch R = 1 ,4427.571,0.000000,0.000000,0.000000
XS GIS Cut Line= 4
822847.111301482782002.440300137822787.381027341782139.484242991
 822697.86492008782346.950985715 822713.69327575 782525.58528544
#Sta/Elev= 30
9673.863304.1903 9779.26299.49699807.557 299.3429829.368 297.6469851.147292.2737
9862.038289.03469879.851285.31219894.712282.97689927.385281.65459938.276276.3395
9955.577276.1226 9970.95273.11559981.841273.55189992.732271.256710003.62268.0861
10014.51271.871110025.41277.3038 10036.3279.753410057.39277.190310067.43276.9078
10087.51279.406810097.55279.758310107.59280.845910127.67280.881910167.82281.9689
10177.86282.9019 10187.9284.893610197.94287.739410218.02 292.10210228.65295.4902
#Mann= 3 , 0 , 0
9673.863    0.04       09673.863    0.04       010228.65    0.04       0
#XS Ineff= 2 , 0
       0                               0
Bank Sta=9673.863,10228.65
Exp/Cntr=0.3,0.1